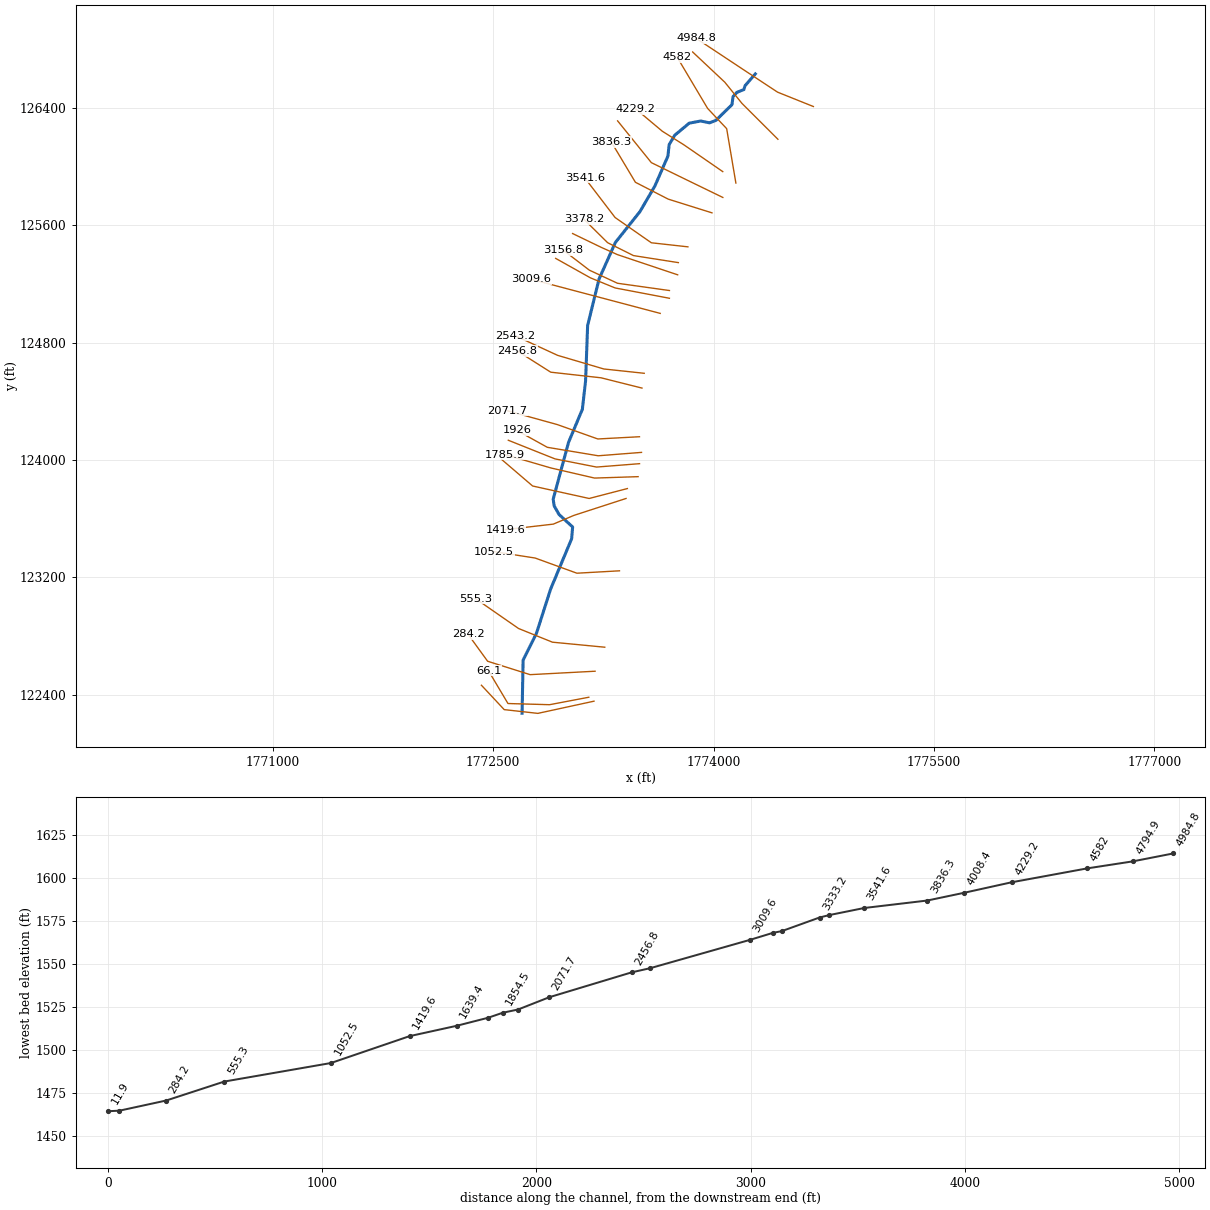
--- Clear Fork Branch.prj (project) ---

Proj Title=Clear Fork Branch
Current Plan=p01
Default Exp/Contr=0,0
English Units
Geom File=g01
Flow File=f01
Plan File=p01
BEGIN DESCRIPTION:
END DESCRIPTION:
DSS Export Rating Curves= 0
DSS Export Rating Curve Sorted= 0
DSS Export Volume Flow Curves= 0
DXF OffsetX= 0
DXF OffsetY= 0
DXF ScaleX= 0
DXF ScaleY= 0

--- Clear Fork Branch.p01 (plan) ---

Plan Title=Floodplain
Program Version=4.00
Geom File=g01
Flow File=f01
K Sum by GR=0
Std Step Tol=0.01
Critical Tol=0.01
Num of Std Step Trials=20
Max Error Tol=0.3
Flow Tol Ratio=0.001
Split Flow NTrial=30
Split Flow Tol=0.02
Split Flow Ratio=0.02
Log Output Level=0
Friction Slope Method=1
Unsteady Friction Slope Method=2
Unsteady Bridges Friction Slope Method=1
Global Log Level=0
CheckData=False
Run HTab=0
Run UNet=0
Run PostProcess=0
UNET Theta=0
UNET Theta Warmup=0
UNET ZTol=0
UNET ZSATol=0
UNET MxIter=0
UNET MaxInSteps=0
UNET DtIC=0
UNET DtMin=0
UNET MaxCRTS=0
UNET WFStab=0
UNET SFStab=0
UNET WFX=0
UNET SFX=0
UNET DSS MLevel=0
UNET DZMax Abort=0
UNET Convert EG Bridges=0
UNET Use Existing IB Tables=0
UNET Froude Limit=0
UNET Froude Power=0
Write IC File=0
Echo Input=False
Echo Output=False
Write Detailed=0

--- Clear Fork Branch.f01 (steady flow) ---

Flow Title=NFF Regression Equation
Program Version=4.00
Number of Profiles=1
Profile Names=P100yr
River Rch & RM=Clear Fork Br...,Main      ,4984.8
563.9991
River Rch & RM=Clear Fork Br...,Main      ,4008.4
572.9949
River Rch & RM=Clear Fork Br...,Main      ,3541.6
634.9494
River Rch & RM=Clear Fork Br...,Main      ,2071.7
672.7145
River Rch & RM=Clear Fork Br...,Main      ,284.2
727.9986
Boundary for River Rch & Prof#=Clear Fork Br...,Main      ,1
Up Type=0
Dn Type=3
Dn Slope=0.022257

--- Clear Fork Branch.g01 (geometry) ---

Geom Title=USGS 10m DEM
Program Version=4.00

River Reach=Clear Fork Br...,Main
Reach XY= 30
     1774283.983      126633.791     1774213.805      126553.124
     1774206.075      126527.028     1774158.047      126507.691
     1774132.233      126478.779     1774125.005      126424.054
     1774015.554      126316.668     1773972.186      126300.147
     1773912.298      126312.538     1773834.309      126298.066
     1773735.704      126215.729     1773697.591      126151.798
     1773688.985      126073.113     1773600.262      125868.944
     1773498.242      125694.035      1773331.58      125484.376
     1773220.415      125235.241     1773142.652      124917.941
      1773128.77      124540.838     1773106.782      124346.492
     1773012.444      124120.189     1772908.219       123733.44
     1772914.931      123687.678     1772947.879      123629.103
     1773040.608      123543.741     1773033.805      123463.342
     1772890.942      123120.719     1772794.463      122818.915
     1772703.551      122635.853     1772696.492      122273.095

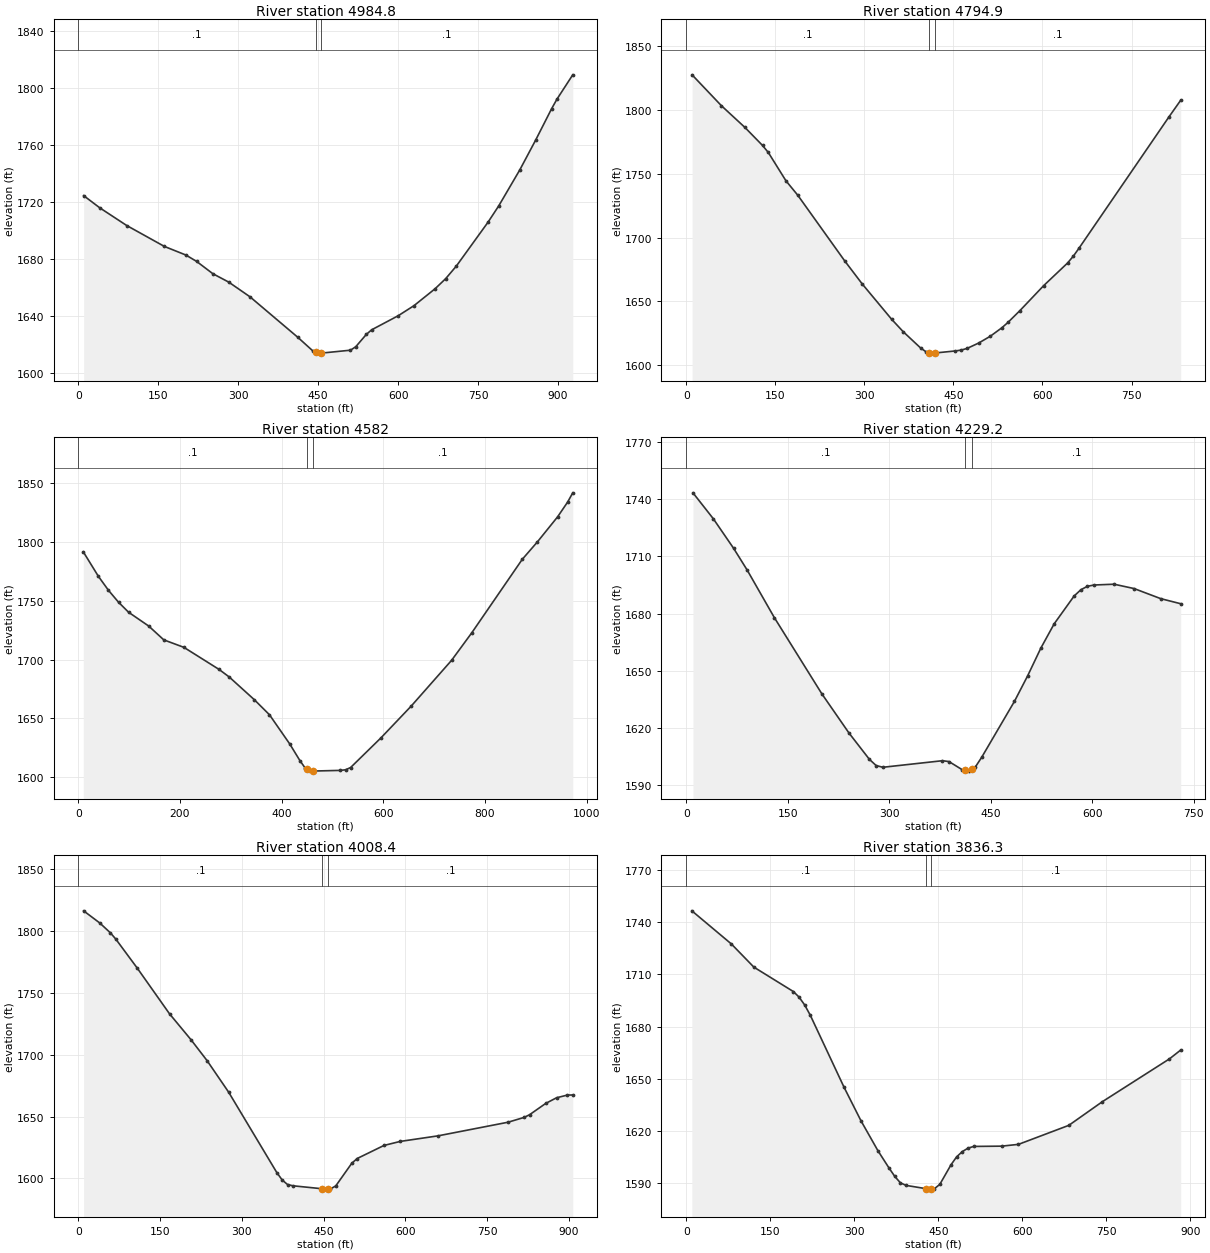
Type RM Length L Ch R = 1 ,4984.8  ,195.7,189.9,184.2
XS GIS Cut Line= 4
     1774679.165      126411.398     1774435.542       126509.23
     1774203.737      126662.349      1773881.21      126876.441
#Sta/Elev= 30
    10.1 1724.52    40.4 1715.94    90.9 1703.55   161.6 1688.88   201.9 1682.85
   222.1 1678.35   252.4 1669.77   282.4 1663.83   322.1 1653.56   411.4 1625.29
   441.1 1615.25     446 1614.66     451 1614.07     456 1614.08   510.6 1616.13
   520.5 1618.55   540.3  1627.2   550.3 1630.42   599.9 1640.25   629.7 1647.35
   669.4 1659.26   689.2 1666.31   709.1 1675.09   768.6  1705.9   788.5 1717.23
   828.2 1742.58     858 1763.52   887.8 1785.42   897.7 1792.06   927.5 1809.22
#Mann= 3 , 0 , 0
       0      .1       0     446    .045       0     456      .1       0
Bank Sta=446,456
XS Rating Curve= 0 ,0
Exp/Cntr=0.3,0.1

Type RM Length L Ch R = 1 ,4794.9  ,211.4,212.9,214.5
XS GIS Cut Line= 4
     1774437.669      126188.105     1774193.104       126432.67
     1774076.138      126577.283     1773857.093      126783.568
#Sta/Elev= 30
     9.9  1827.5    59.3  1803.3    98.8 1786.33   128.5 1772.19   138.3 1766.65
     168 1744.47   187.8 1733.23   266.8 1681.81   296.5 1663.62   345.9 1636.02
   365.4 1626.26   394.8 1613.48   404.6 1610.29   409.4 1609.88   414.4 1609.45
   419.4 1609.57   453.5 1611.17   463.3 1611.85   473.1 1613.15   492.7 1617.38
   512.3 1622.73   531.9 1629.41   541.9 1633.52     562 1642.75   602.1 1662.36
   642.2 1680.02   652.2 1685.55   662.2  1692.1   812.7 1794.32   832.8 1807.57
#Mann= 3 , 0 , 0
       0      .1       0   409.4    .045       0   419.4      .1       0
Bank Sta=409.4,419.4
XS Rating Curve= 0 ,0
Exp/Cntr=0.3,0.1

Type RM Length L Ch R = 1 ,4582    ,347.7,352.8,357.9
XS GIS Cut Line= 4
     1774151.544      125889.584     1774088.898      126260.411
     1773959.172      126398.644     1773751.459      126748.673
#Sta/Elev= 30
     9.9  1791.3    39.6 1770.52    59.4  1758.7    79.2 1748.58      99 1740.08
   138.6 1728.37   168.2 1716.67   207.8 1710.33   277.1 1691.57   296.9 1685.21
   346.4  1665.9   376.1 1653.18     416 1628.41   435.9 1614.37   445.9 1608.25
   450.9 1606.82   455.9 1605.38   460.9 1605.43   515.8 1606.01   525.7 1606.51
   535.7 1608.43   595.4 1633.58     655 1660.56   734.4 1699.35   774.1 1722.68
   873.4 1784.96   903.2 1799.76   942.9 1820.97   962.7 1833.54   972.7 1841.33
#Mann= 3 , 0 , 0
       0      .1       0   450.9    .045       0   460.9      .1       0
Bank Sta=450.9,460.9
XS Rating Curve= 0 ,0
Exp/Cntr=0.3,0.1

Type RM Length L Ch R = 1 ,4229.2  ,218.6,220.8,223
XS GIS Cut Line= 4
     1774062.472      125967.363     1773798.555      126149.706
     1773651.401      126242.477     1773470.658      126394.429
#Sta/Elev= 30
      10 1743.34    40.1 1729.73    70.2 1714.16    90.2 1702.77   130.3 1677.86
   200.5 1637.88   240.6 1617.32   270.7 1603.54   280.7 1600.26   290.7 1599.34
   378.8 1602.79   388.4 1602.34   407.8  1598.1   412.4 1597.72   417.4 1597.32
   422.4 1598.36   427.1 1599.34   436.8  1604.6   485.1 1633.88   504.6 1647.26
   524.3 1661.94   543.9 1674.61   573.4 1689.21   583.3 1692.48   593.1 1694.31
     603 1694.98   632.5 1695.39     662 1693.11   701.4 1687.82   730.9 1685.15
#Mann= 3 , 0 , 0
       0      .1       0   412.4    .045       0   422.4      .1       0
Bank Sta=412.4,422.4
XS Rating Curve= 0 ,0
Exp/Cntr=0.3,0.1

Type RM Length L Ch R = 1 ,4008.4  ,172.6,172.1,171.6
XS GIS Cut Line= 4
     1774062.714      125791.291     1773814.744      125912.018
     1773576.374      126028.606     1773346.696      126313.578
#Sta/Elev= 30
     9.8 1816.51    39.4 1806.69    59.1 1798.63    68.9 1793.61   108.3 1770.09
   167.4 1733.17   206.8  1712.2   236.4 1695.22   275.8  1669.8   364.2  1604.7
   374.1 1598.65   383.9    1595   393.7 1593.97   447.7 1591.55   452.7 1591.26
   457.7 1591.33   462.5 1591.39   472.4 1593.85   501.8 1612.19   511.7 1616.04
   560.9 1626.62   590.6 1629.87   659.9 1634.37   788.5 1645.41   818.1 1649.33
     828 1651.49   857.7 1660.66   877.5 1665.21   897.3 1667.38   907.2 1667.46
#Mann= 3 , 0 , 0
       0      .1       0   447.7    .045       0   457.7      .1       0
Bank Sta=447.7,457.7
XS Rating Curve= 0 ,0
Exp/Cntr=0.3,0.1

Type RM Length L Ch R = 1 ,3836.3  ,297.4,294.7,291.9
XS GIS Cut Line= 4
     1773988.945      125686.215     1773691.213      125779.788
     1773467.915      125894.627     1773304.163      126168.965
#Sta/Elev= 30
    10.1 1746.42    80.5 1727.45   120.8 1714.12   191.3 1700.11   201.3 1696.98
   211.4 1692.46   221.5 1686.53   281.9 1645.12   312.1  1625.9   342.2 1608.82
   362.3 1598.75   372.4 1594.04   382.4 1590.36   392.4 1588.91   427.6 1587.05
   432.6 1586.76   437.6 1586.84   442.7 1586.92   452.7 1589.48   472.8 1600.78
   482.8  1605.3   492.9  1608.3   502.9 1610.23     513 1611.25   563.2 1611.42
   593.1 1612.44     683 1623.35   742.9 1636.93   862.7  1661.5   882.7 1666.55
#Mann= 3 , 0 , 0
       0      .1       0   427.6    .045       0   437.6      .1       0
Bank Sta=427.6,437.6
XS Rating Curve= 0 ,0
Exp/Cntr=0.3,0.1

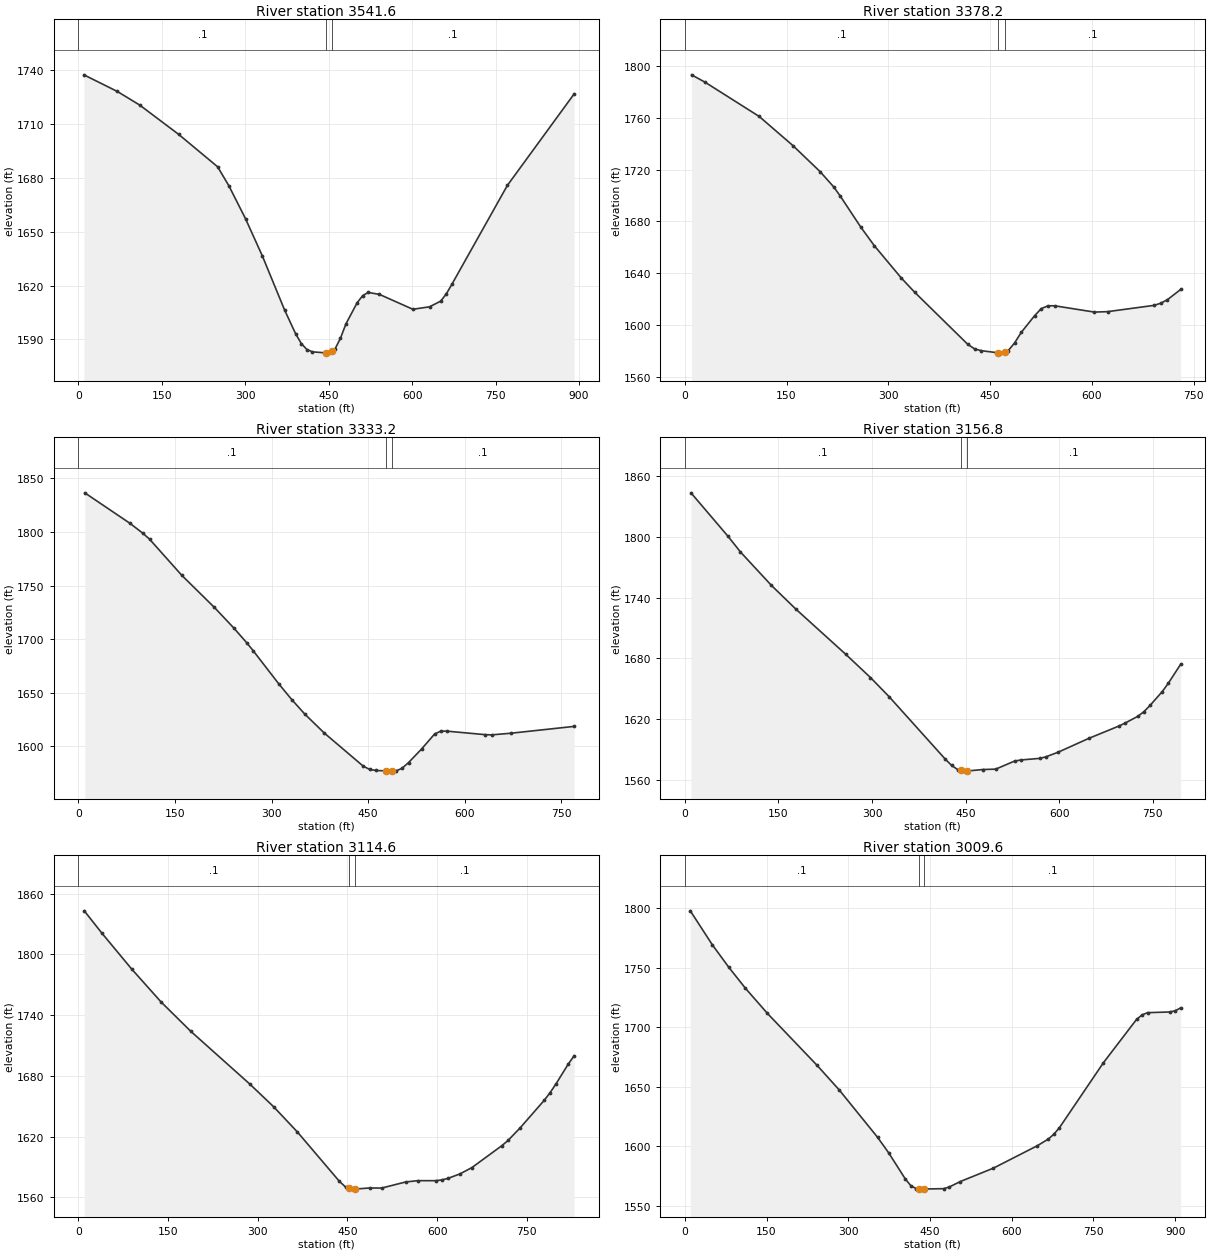
Type RM Length L Ch R = 1 ,3541.6  ,160.5,163.4,166.3
XS GIS Cut Line= 4
     1773825.193       125454.41     1773576.374      125482.056
     1773329.682      125654.315     1773123.397        125924.4
#Sta/Elev= 30
      10 1737.16    70.1 1727.91   110.2 1720.37   180.3 1704.06   250.3 1686.03
   270.4 1675.56   300.5 1657.14   330.6 1636.54   370.7 1606.39   390.8 1593.01
   400.8 1587.73   410.8 1584.42   420.8 1583.13   445.9 1582.54   450.9 1582.42
   455.9 1583.46     461 1584.52     471 1590.64     481 1598.72   501.1 1610.44
   511.1 1614.41   521.1 1616.17   541.2 1615.07   601.2 1606.81   631.2 1608.17
   651.2 1611.33   661.2  1615.3   671.2 1620.62   771.1 1675.69   891.1 1726.57
#Mann= 3 , 0 , 0
       0      .1       0   445.9    .045       0   455.9      .1       0
Bank Sta=445.9,455.9
XS Rating Curve= 0 ,0
Exp/Cntr=0.3,0.1

Type RM Length L Ch R = 1 ,3378.2  ,44.2,45,45.9
XS GIS Cut Line= 4
     1773760.167      125346.758     1773454.663      125394.743
     1773278.719      125482.716     1773118.769      125641.066
#Sta/Elev= 30
      10  1793.1    29.9  1787.4   109.7 1760.97   159.6  1738.4   199.5 1718.38
   219.5 1706.65   229.4 1699.38   259.4 1675.62   279.3 1661.29   319.1 1636.35
   338.8 1625.36   417.4    1585   427.3 1581.57   437.1  1580.2   461.6 1578.58
   466.6 1578.31   471.6 1579.18   476.5 1580.03   486.3 1586.22   496.1 1594.36
   515.7 1607.19   525.5 1612.64   535.3 1614.82   545.1 1614.86   603.8 1609.99
   623.4 1610.32   691.9 1615.18   701.7 1616.84   711.5 1619.54     731 1627.43
#Mann= 3 , 0 , 0
       0      .1       0   461.6    .045       0   471.6      .1       0
Bank Sta=461.6,471.6
XS Rating Curve= 0 ,0
Exp/Cntr=0.3,0.1

Type RM Length L Ch R = 1 ,3333.2  ,176.7,176.4,176.1
XS GIS Cut Line= 4
     1773755.369      125263.585     1773345.897      125401.141
     1773235.532      125450.726     1773040.393      125545.096
#Sta/Elev= 30
      10 1836.56    80.4 1808.01   100.5 1798.66   110.5 1793.36   160.7 1759.53
     211 1729.77   241.1 1710.61   261.2 1696.83   271.2 1689.43   311.4 1658.14
   331.5 1643.52   351.6  1630.1   381.7 1612.52     442 1581.69   452.1  1578.5
   462.2 1577.53   477.4 1577.11   482.4 1576.91   487.4 1576.95   492.5 1576.99
   502.5 1579.51   512.6 1584.88   532.8 1597.53     553  1611.5   562.8 1614.28
   572.7 1614.18   631.8 1610.93   641.6 1610.75   671.2 1612.25   769.7 1618.65
#Mann= 3 , 0 , 0
       0      .1       0   477.4    .045       0   487.4      .1       0
Bank Sta=477.4,487.4
XS Rating Curve= 0 ,0
Exp/Cntr=0.3,0.1

Type RM Length L Ch R = 1 ,3156.8  ,41.4,42.2,43.1
XS GIS Cut Line= 4
     1773699.386      125156.418     1773345.897      125206.003
     1773153.958      125295.575     1772974.814      125433.131
#Sta/Elev= 30
     9.9 1843.23    69.4  1800.3    89.2 1784.95   138.8 1752.03   178.5 1728.36
   257.8 1684.21   297.5 1661.26   327.2 1642.52   417.5 1580.79   427.6 1574.63
   437.6 1570.43   442.7 1569.71   447.7 1569.01   452.7 1569.15     478  1570.6
   498.2 1570.96   528.4  1578.9   538.5    1580   568.8 1581.57   578.6 1583.09
   598.2 1587.63   647.3 1601.25   696.4 1613.61   706.2 1616.54   725.9 1622.99
   735.7 1627.55   745.5 1633.68   765.2 1647.42     775 1655.71   794.6 1674.25
#Mann= 3 , 0 , 0
       0      .1       0   442.7    .045       0   452.7      .1       0
Bank Sta=442.7,452.7
XS Rating Curve= 0 ,0
Exp/Cntr=0.3,0.1

Type RM Length L Ch R = 1 ,3114.6  ,102.3,105,107.7
XS GIS Cut Line= 4
     1773699.386      125103.635     1773329.902      125174.013
     1773161.955      125242.791      1772925.23      125375.549
#Sta/Elev= 30
     9.9 1843.11    39.6 1820.89    89.1 1785.64   138.6 1752.84   188.1 1723.97
     287 1671.69   326.6 1649.38   366.2 1624.52   436.6 1575.61   446.7 1570.13
   451.8 1569.04   456.8 1567.98   461.8 1568.01     487 1569.11   507.2 1569.04
   547.5 1575.09   567.7 1576.35   597.8 1576.32   607.9 1577.12   617.9 1578.58
     638 1583.03   658.1  1589.3   708.4 1611.07   718.4 1616.08   738.6 1628.48
   778.8 1655.68   788.8 1663.38   798.9 1672.28     819  1691.5     829 1699.83
#Mann= 3 , 0 , 0
       0      .1       0   451.8    .045       0   461.8      .1       0
Bank Sta=451.8,461.8
XS Rating Curve= 0 ,0
Exp/Cntr=0.3,0.1

Type RM Length L Ch R = 1 ,3009.6  ,467.2,466.4,465.8
XS GIS Cut Line= 3
     1773636.573      125000.571      1773196.77      125117.184
     1772756.968      125233.798
#Sta/Elev= 30
    10.1 1797.66    50.6 1769.09    80.9 1750.18   111.2 1732.69   151.7  1711.5
   242.7 1667.96   283.1 1647.44   353.9 1607.46   374.1 1594.51   404.4 1572.75
   414.6 1566.99   424.7 1564.36   429.8 1564.17   434.8 1563.99   439.8 1564.08
   475.2 1564.39   485.3 1565.76   505.6 1570.36   566.2 1581.57   647.1 1600.45
   667.3 1606.08   677.4 1610.12   687.6 1615.58   768.4 1670.19   829.1 1706.48
   839.2 1710.26   849.3 1712.15   889.8 1712.73   899.9 1713.72     910 1716.13
#Mann= 3 , 0 , 0
       0      .1       0   429.8    .045       0   439.8      .1       0
Bank Sta=429.8,439.8
XS Rating Curve= 0 ,0
Exp/Cntr=0.3,0.1

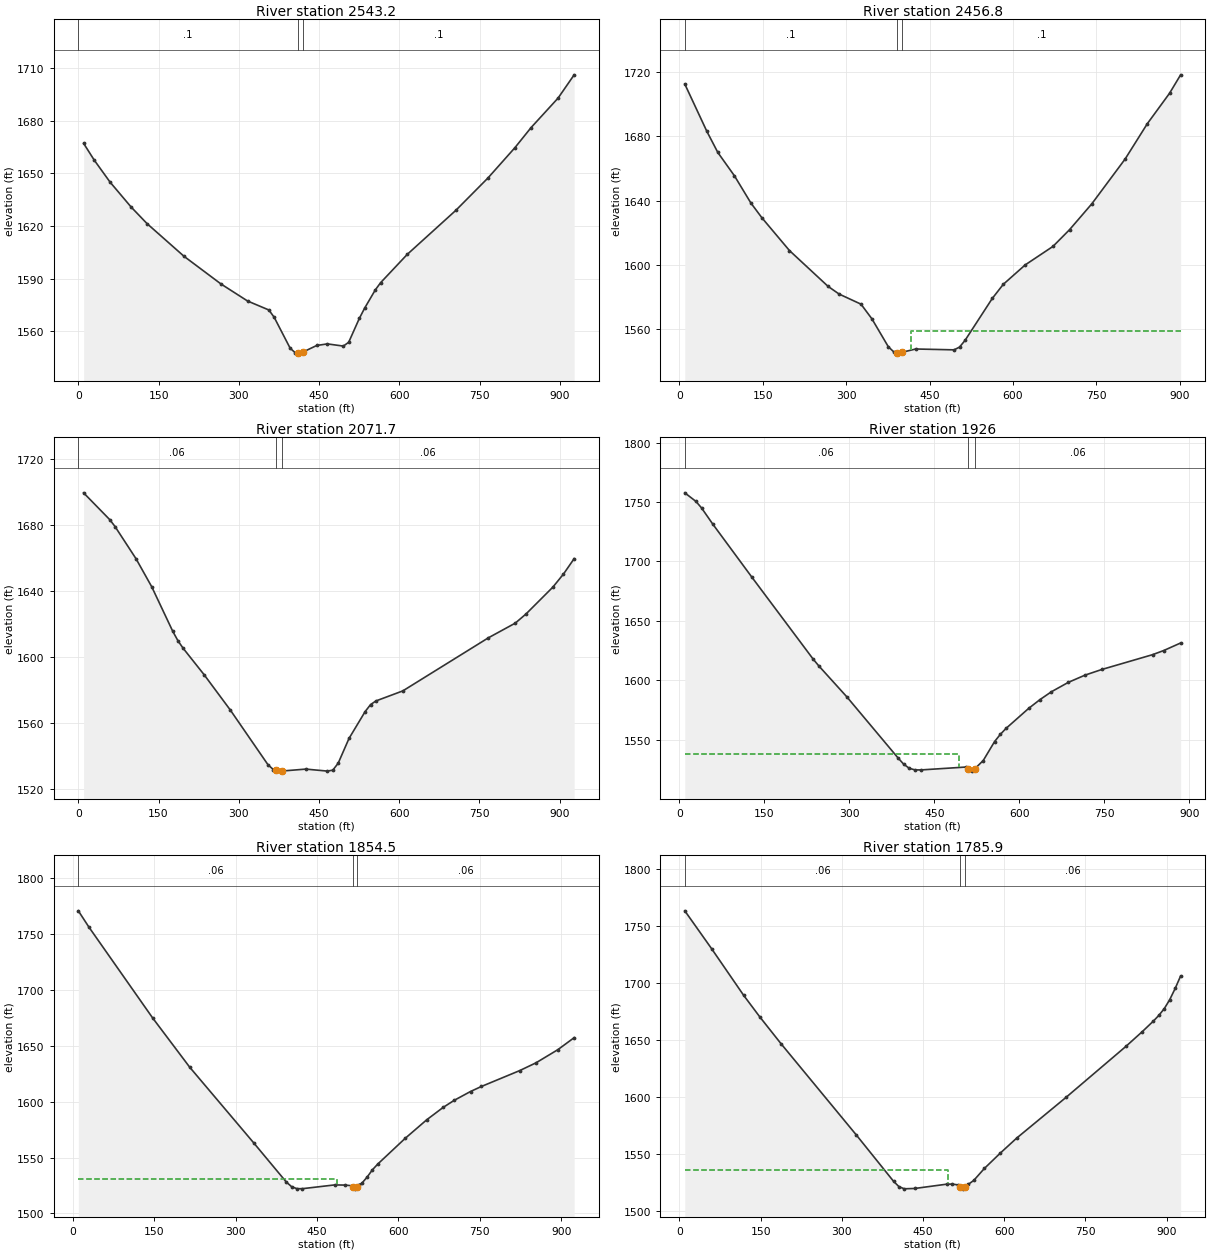
Type RM Length L Ch R = 1 ,2543.2  ,82.6,86.4,90
XS GIS Cut Line= 4
     1773527.844      124591.962     1773252.964      124621.403
     1772938.378      124714.334     1772646.285      124849.543
#Sta/Elev= 30
     9.9 1667.17    29.6 1657.67    59.2 1645.11    98.7 1630.84   128.4  1621.4
   197.5 1602.75   266.6 1586.96   316.2 1577.26     356 1572.14   365.9 1567.97
   395.7 1550.36   405.7 1547.61   410.6 1547.57   415.6 1547.54   420.6 1548.29
   445.4 1551.91   465.3  1552.8   495.1 1551.56   505.1 1553.74     525 1567.37
   534.9  1573.2   554.8  1583.6   564.7 1587.71   614.5 1603.86   705.1 1628.93
   765.4 1647.48   815.7 1664.74   845.9 1676.21   896.2 1692.98   926.3 1706.27
#Mann= 3 , 0 , 0
       0      .1       0   410.6    .045       0   420.6      .1       0
Bank Sta=410.6,420.6
XS Rating Curve= 0 ,0
Exp/Cntr=0.3,0.1

Type RM Length L Ch R = 1 ,2456.8  ,389.7,385.1,380.4
XS GIS Cut Line= 4
     1773512.575      124491.035     1773233.983      124561.215
     1772891.592      124599.495      1772664.04      124744.107
#Sta/Elev= 30
     9.9 1712.51    49.5 1683.13    69.3 1669.94    99.1 1655.46   128.8 1638.48
   148.6 1629.29   198.1 1608.93   267.5 1586.66   287.3 1581.88   326.7 1575.59
   346.4 1566.42   375.9 1549.07   385.7 1545.89   390.6 1545.51   395.6 1545.13
   400.6 1545.66   425.1  1547.7     494 1547.17   503.9 1548.89   513.7 1553.02
   562.9 1579.23   582.6 1587.95     622 1600.02   671.8  1611.5   701.7 1621.92
   741.7    1638   801.6 1665.87   841.5 1687.84   881.5 1706.78   901.4 1718.25
#Mann= 3 , 0 , 0
     9.9      .1       0   390.6    .045       0   400.6      .1       0
#XS Ineff= 2 , 0
                          417.09         1558.81
Permanent Ineff=
       F       F
Bank Sta=390.6,400.6
XS Rating Curve= 0 ,0
Exp/Cntr=0.3,0.1

Type RM Length L Ch R = 1 ,2071.7  ,142.2,145.8,149.3
XS GIS Cut Line= 4
     1773495.561      124159.277      1773211.84      124144.043
     1772936.251      124242.217     1772598.541      124335.792
#Sta/Elev= 30
     9.8 1699.22    58.8 1682.96    68.6 1678.82   107.8 1659.35   137.2 1642.36
   176.4 1615.47   186.2 1609.67     196 1605.08   235.1 1589.12   284.1 1567.73
   354.7 1534.52   364.8  1531.6   369.9 1531.14   374.9 1530.69   379.9 1530.72
   425.4 1531.92   465.7 1530.71   475.8 1531.28   485.9  1535.5   506.1 1550.47
   536.3 1566.76   546.4 1570.97   556.5  1573.2   606.7 1579.27   766.9 1611.46
     817 1620.31     837 1625.84   887.1 1642.05   907.1 1650.02   927.1 1659.38
#Mann= 3 , 0 , 0
       0     .06       0   369.9    .045       0   379.9     .06       0
Bank Sta=369.9,379.9
XS Rating Curve= 0 ,0
Exp/Cntr=0.3,0.1

Type RM Length L Ch R = 1 ,1926    ,72,71.4,70.8
XS GIS Cut Line= 4
     1773509.305      124052.514     1773214.809      124029.416
     1772868.343       124087.16     1772660.464      124202.649
#Sta/Elev= 30
     9.8 1757.77    29.5 1750.53    39.4 1745.03    59.1 1731.48     128 1686.87
   236.3 1617.78   246.2 1612.13   295.4 1586.21   385.7 1534.81   395.8 1529.48
   405.8 1525.93   415.8 1524.62   425.9 1524.55   506.1 1527.01     509 1525.76
  515.98 1523.56  521.84 1525.76   536.3  1532.5   556.3 1548.43   566.4 1554.49
   576.4 1559.47   616.5 1576.39   636.6 1583.83   656.6 1590.37   686.3 1598.24
     716 1604.38   745.7 1609.14   834.9 1621.55   854.7 1625.05   884.5  1631.4
#Mann= 3 , 0 , 0
     9.8     .06       0     509    .045       0  521.84     .06       0
#XS Ineff= 2 , 0
           494.2 1538.39
Permanent Ineff=
       F       F
Bank Sta=509,521.84
XS Rating Curve= 0 ,0
Exp/Cntr=0.3,0.1

Type RM Length L Ch R = 1 ,1854.5  ,69.3,68.7,68
XS GIS Cut Line= 4
     1773495.831      123975.521      1773203.26      123952.424
     1772920.313      124008.243      1772602.72       124135.28
#Sta/Elev= 30
     9.8    1771    29.3 1756.43   146.7  1675.1   215.2 1630.87   333.3 1563.03
   392.9 1528.22   402.9  1523.9   412.8 1522.09   422.8 1522.08   482.4 1525.47
   502.3  1525.3   514.3  1524.7  516.18 1523.87  520.28 1521.69  523.81 1523.93
  526.72 1525.66   532.2 1526.81   542.1 1532.39     552 1539.01     562 1544.23
   612.1 1567.06   652.3 1583.89   682.5 1594.94   702.6 1601.19   732.8 1609.14
   752.9 1613.65   823.3 1627.83   853.5 1634.82   893.8 1646.61   923.9 1657.37
#Mann= 3 , 0 , 0
     9.8     .06       0  516.18    .045       0  523.81     .06       0
#XS Ineff= 2 , 0
          486.16 1530.68
Permanent Ineff=
       F       F
Bank Sta=516.18,523.81
XS Rating Curve= 0 ,0
Exp/Cntr=0.3,0.1

Type RM Length L Ch R = 1 ,1785.9  ,146.3,146.5,146.7
XS GIS Cut Line= 4
     1773486.207       123886.98     1773189.786      123877.356
     1772891.441      123946.649     1772581.547      124037.115
#Sta/Elev= 30
     9.9 1762.97    59.3 1729.82   118.6 1688.83   148.3 1669.98   187.8 1646.27
   326.2 1566.59   395.4 1525.69   405.3 1521.01   415.1 1519.06   434.9 1519.36
   494.2 1523.15   504.1 1523.16   513.9 1522.54   518.7  1520.8  523.86 1518.77
  528.15 1520.67   533.7 1523.04   543.6 1526.39   563.3 1536.95     593 1550.54
     623 1563.59   713.8 1599.18   824.8 1644.08   855.1 1657.05   875.3 1666.19
   885.3 1671.14   895.4 1677.07   905.5 1684.95   915.6 1694.83   925.7 1705.82
#Mann= 3 , 0 , 0
     9.9     .06       0   518.7    .045       0  528.15     .06       0
#XS Ineff= 2 , 0
          496.16 1535.86
Permanent Ineff=
       F       F
Bank Sta=518.7,528.15
XS Rating Curve= 0 ,0
Exp/Cntr=0.3,0.1

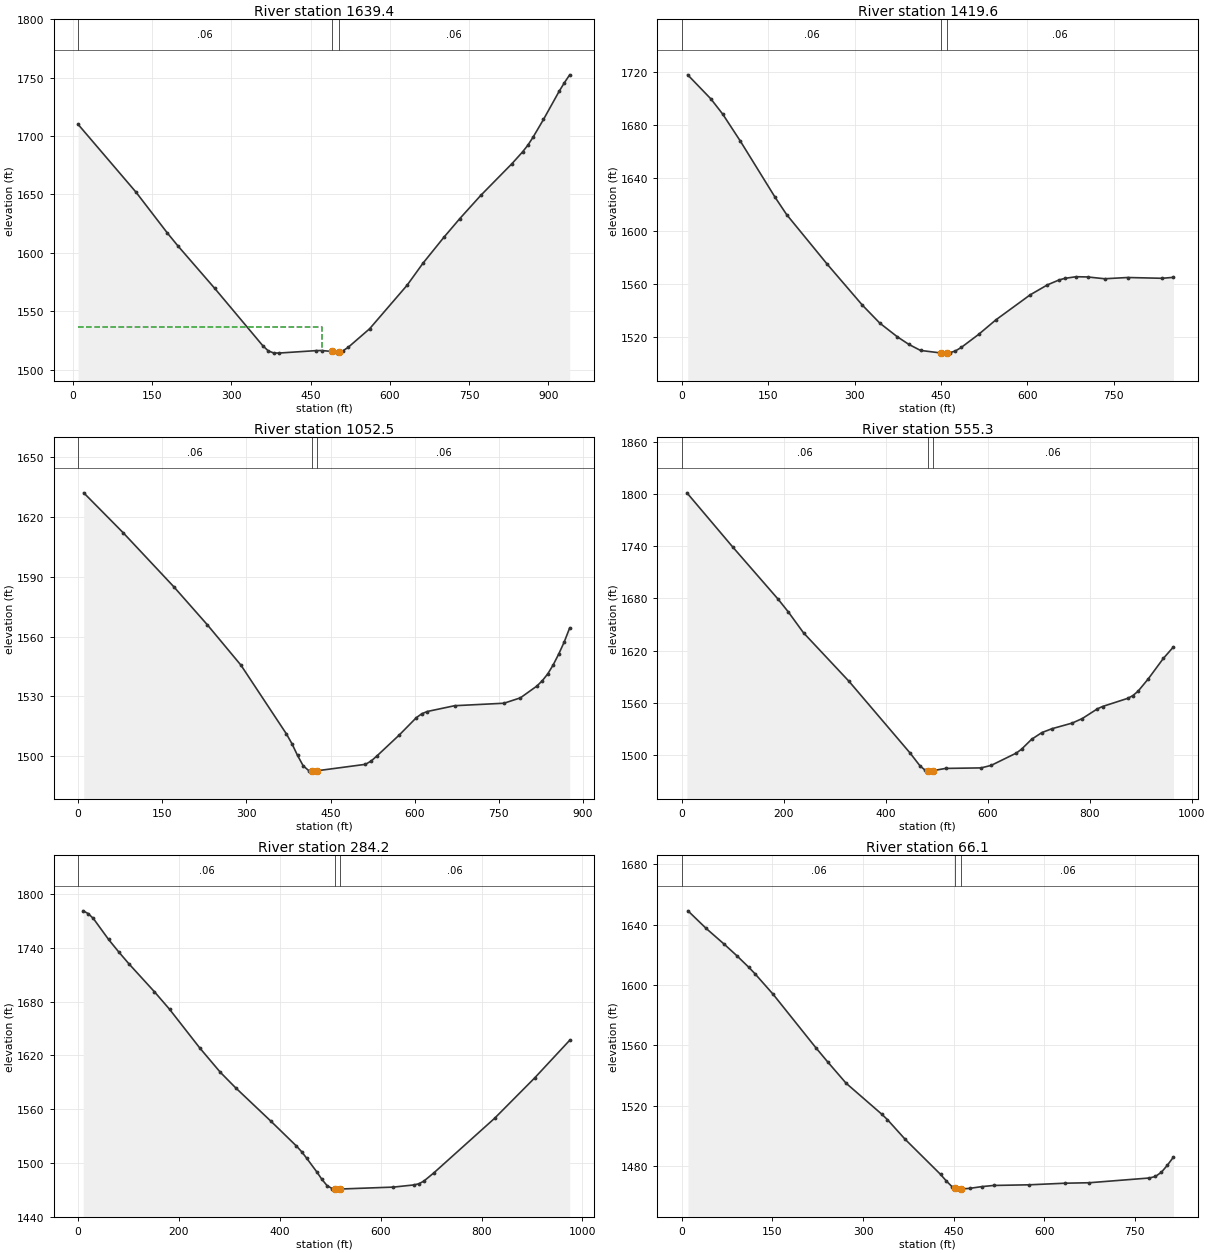
Type RM Length L Ch R = 1 ,1639.4  ,207.4,219.7,232
XS GIS Cut Line= 4
     1773413.197       123805.83      1773153.17        123738.2
     1772768.246      123823.266     1772557.707      124004.032
#Sta/Elev= 30
      10 1710.05   119.4 1652.09   179.1  1616.9     199 1605.91   268.7 1569.52
   359.6 1520.44   369.8  1516.1   379.9 1514.29     390 1514.18   460.7 1516.27
   470.8 1516.36   491.1 1515.52  499.62 1514.12  503.46 1515.07   511.3 1516.09
   521.4 1519.18   561.8 1535.02   632.6 1572.24   662.9 1591.24   702.5 1613.46
   732.3 1629.29   771.9 1649.14   831.4 1676.53   851.2 1686.48   861.1 1692.15
     871 1699.03   890.8 1714.27   920.6 1738.52   930.5 1745.83   940.4  1752.5
#Mann= 3 , 0 , 0
      10     .06       0   491.1    .045       0  503.46     .06       0
#XS Ineff= 2 , 0
          471.65 1536.74
Permanent Ineff=
       F       F
Bank Sta=491.1,503.46
XS Rating Curve= 0 ,0
Exp/Cntr=0.3,0.1

Type RM Length L Ch R = 1 ,1419.6  ,383.4,367.1,350.4
XS GIS Cut Line= 4
     1773404.115        123738.2     1773048.391        123622.5
     1772909.235      123563.319     1772583.227      123525.534
#Sta/Elev= 30
    10.1 1717.67    50.5 1699.48    70.8 1688.16   101.1 1668.06   161.8  1625.5
     182 1612.38   252.7 1574.91   313.4 1544.25   343.7  1530.7   374.1 1520.42
   394.2 1514.67   414.4 1510.15   449.7 1508.24   454.7 1508.12   459.7 1508.23
   464.8 1508.35   474.9 1509.76     485 1512.37   515.2 1522.21   545.2 1533.17
   604.8 1552.02   634.7 1559.52   654.6 1563.16   664.5 1564.38   684.4 1565.65
   704.3 1565.48   734.1 1564.12   773.9 1565.06   833.6 1564.47   853.5 1565.17
#Mann= 3 , 0 , 0
       0     .06       0   449.7    .045       0   459.7     .06       0
Bank Sta=449.7,459.7
XS Rating Curve= 0 ,0
Exp/Cntr=0.3,0.1

Type RM Length L Ch R = 1 ,1052.5  ,498,497.2,496.5
XS GIS Cut Line= 4
     1773359.456      123244.816     1773069.656      123228.525
     1772785.259      123332.009     1772505.303      123375.665
#Sta/Elev= 30
      10 1632.07    80.1 1612.12   170.2 1585.09   230.2 1565.95   290.3 1545.64
     371 1511.32     381 1506.37   391.1 1500.41   401.2  1495.2   411.3 1492.75
   416.4 1492.64   421.4 1492.54   426.4 1492.74   512.2 1495.95   522.3 1497.61
   532.4  1500.1   572.7 1510.73   602.7  1519.3   612.4 1521.27   622.2 1522.43
   671.1 1525.34     759 1526.58   788.3 1529.28   817.6 1535.17   827.4 1537.88
   837.2 1541.33   846.9 1545.86   856.7 1551.28   866.5 1557.32   876.2 1564.36
#Mann= 3 , 0 , 0
       0     .06       0   416.4    .045       0   426.4     .06       0
Bank Sta=416.4,426.4
XS Rating Curve= 0 ,0
Exp/Cntr=0.3,0.1

Type RM Length L Ch R = 1 ,555.3   ,269.5,271.1,272.6
XS GIS Cut Line= 4
     1773259.503      122723.786      1772903.22      122758.038
     1772672.546      122851.385     1772379.068      123055.544
#Sta/Elev= 30
     9.9 1801.25    99.4 1739.31   188.9 1679.11   208.8 1664.55   238.6 1640.58
   328.1 1584.74   447.5 1502.72   467.4 1487.65   477.4 1482.85   482.3 1482.34
   487.3 1481.81   492.3 1482.33   517.2 1484.92   586.9 1485.52   606.8 1488.41
   656.4 1502.64   666.4 1507.05   686.2 1518.41   706.1 1526.02   725.9 1530.48
   765.7 1536.98   785.5 1542.18   815.3 1553.37   825.2 1555.99   874.9 1565.41
   884.8 1568.55   894.8  1573.5   914.6 1587.47   944.4 1611.12   964.3  1624.4
#Mann= 3 , 0 , 0
       0     .06       0   482.3    .045       0   492.3     .06       0
Bank Sta=482.3,492.3
XS Rating Curve= 0 ,0
Exp/Cntr=0.3,0.1

Type RM Length L Ch R = 1 ,284.2   ,212.6,218.2,223.7
XS GIS Cut Line= 4
     1773193.577      122560.034     1772751.232       122536.64
     1772462.008      122628.087     1772328.028      122813.105
#Sta/Elev= 30
    10.1 1781.32    20.1 1778.16    30.2 1772.78    60.4 1749.38    80.5 1735.49
   100.7 1722.22     151 1691.23   181.2 1671.56   241.6 1628.05   281.9 1601.24
   312.1    1584   382.6 1546.43   432.9  1518.9     443 1512.72   453.1 1505.38
   473.3 1490.02   483.4  1481.7   493.5 1474.83   503.6 1471.46   508.7 1471.14
   513.7 1470.82   518.7 1470.92     625 1473.08   665.4 1475.48   675.5 1476.75
   685.6  1479.8   705.9 1489.23   825.8 1549.84   905.2 1594.85   974.7  1636.9
#Mann= 3 , 0 , 0
       0     .06       0   508.7    .045       0   518.7     .06       0
Bank Sta=508.7,518.7
XS Rating Curve= 0 ,0
Exp/Cntr=0.3,0.1

Type RM Length L Ch R = 1 ,66.1    ,55.8,54.1,52.4
XS GIS Cut Line= 4
     1773150.835      122382.628     1772883.643      122331.706
     1772600.532      122339.703     1772468.388       122562.16
#Sta/Elev= 30
    10.1 1649.05    40.3 1637.38    70.5 1626.84    90.7 1619.47   110.8 1611.71
   120.9  1607.5   151.1 1593.85   221.6 1558.61   241.8 1548.94     272 1534.98
   330.6 1514.65   340.4  1510.9   369.7 1497.91   428.3  1474.7     438 1470.28
   447.8 1466.38   452.6 1465.67   457.6 1464.93   462.6 1465.02   477.1 1465.46
   496.6 1466.59   516.2 1467.36   575.1 1467.79   634.8 1468.85   674.6 1469.16
   774.2  1472.3   784.1  1473.3   794.1 1476.12     804 1480.79     814 1486.11
#Mann= 3 , 0 , 0
       0     .06       0   452.6    .045       0   462.6     .06       0
Bank Sta=452.6,462.6
XS Rating Curve= 0 ,0
Exp/Cntr=0.3,0.1

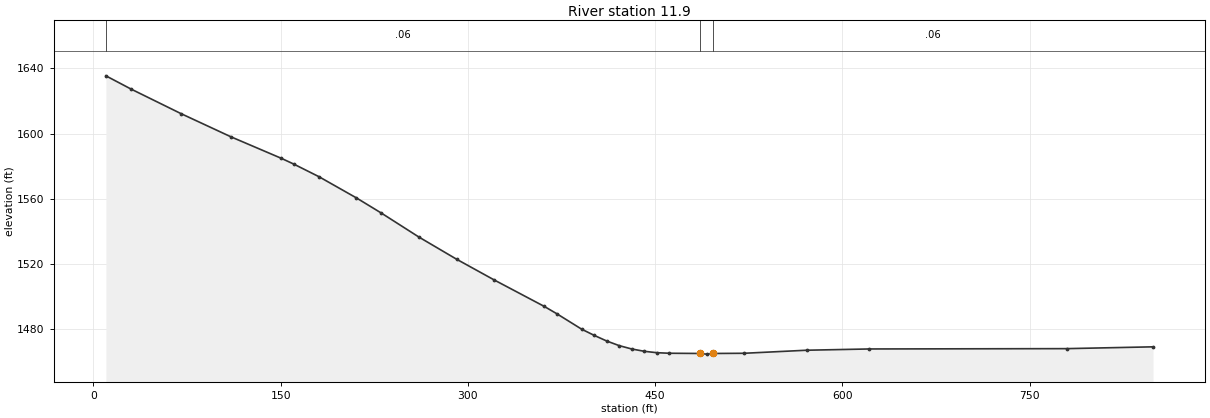
Type RM Length L Ch R = 1 ,11.9    ,18.5,11.9,5.4
XS GIS Cut Line= 4
     1773185.948      122355.698     1772803.668      122272.524
      1772574.94      122298.116     1772419.788      122464.464
#Sta/Elev= 30
      10 1635.49    30.1 1627.38    70.2 1612.27   110.3    1598   150.5 1584.85
   160.5  1581.3   180.6 1573.59   210.7 1560.53   230.7  1551.2   260.8 1536.47
   290.9  1522.9     321 1510.18   361.1 1493.94   371.2 1489.42   391.2 1479.89
   401.2 1476.12   411.2 1472.66   421.2 1469.82   431.3 1467.75   441.3 1466.34
   451.3 1465.48   461.3 1465.14   486.3    1465  491.17  1464.6   496.3    1465
   521.3 1465.12   571.3 1466.99   621.4 1467.77   779.6 1467.97   848.9 1469.08
#Mann= 3 , 0 , 0
      10     .06       0   486.3    .045       0   496.3     .06       0
Bank Sta=486.3,496.3
XS Rating Curve= 0 ,0
Exp/Cntr=0.3,0.1

Chan Stop Cuts=-1
Use User Specified Reach Order=0